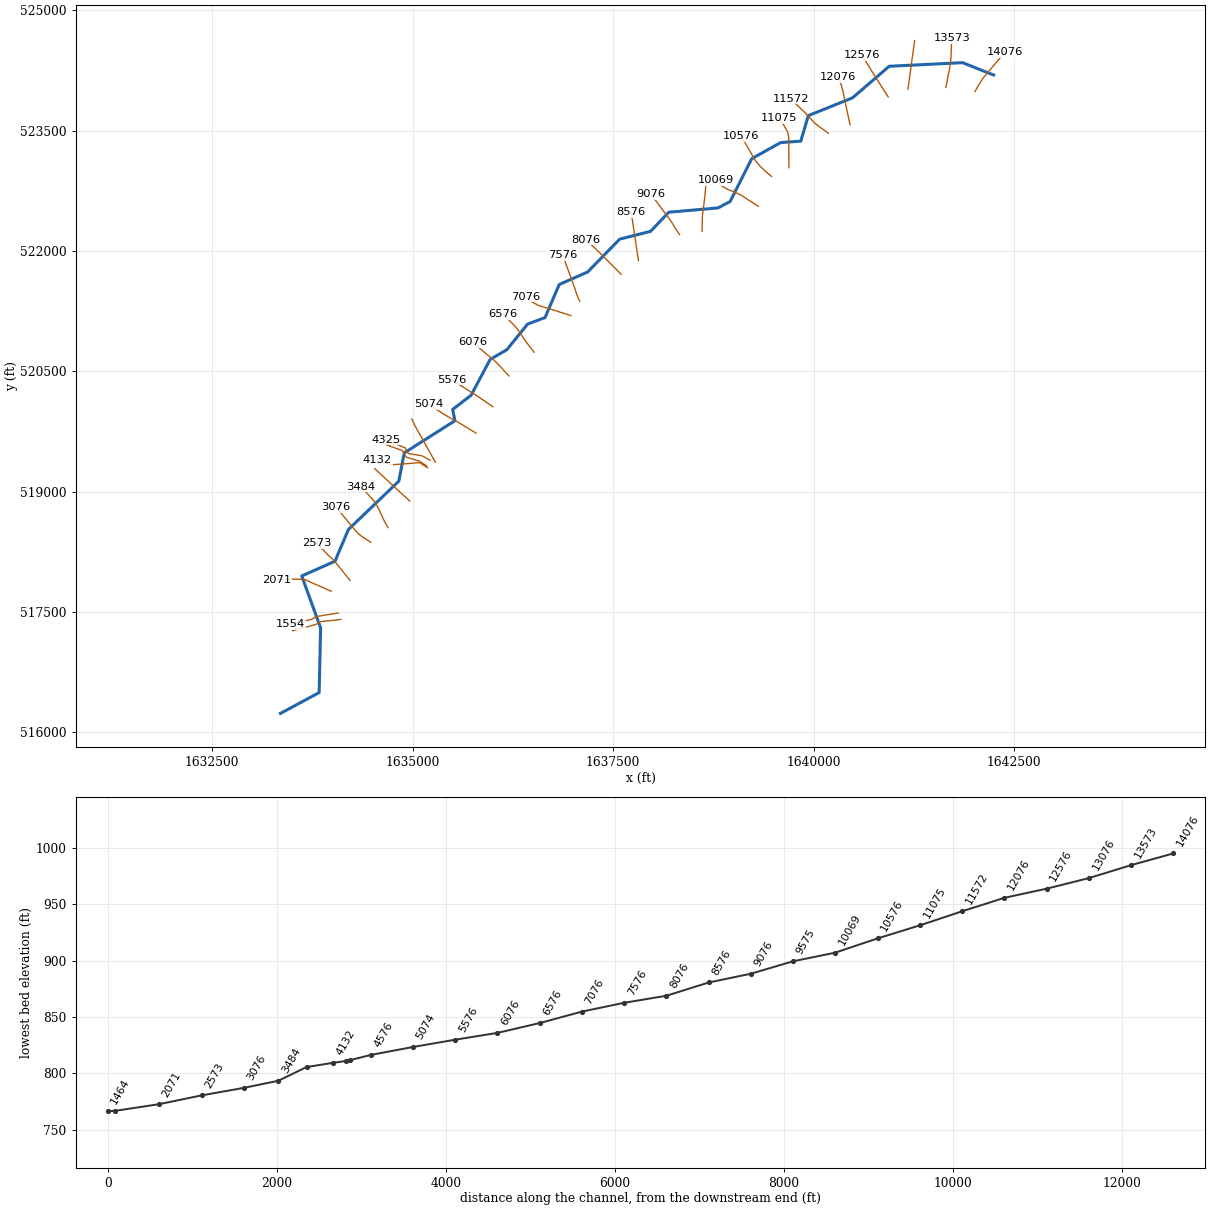
--- TomsRn.prj (project) ---

Proj Title=TomsRn
Current Plan=p01
Default Exp/Contr=0,0
English Units
Geom File=g01
Flow File=f01
Plan File=p01
BEGIN DESCRIPTION:
---------- MODELED AS PART OF WVEM CTP PROGRAM, 2025----------
Stream Name: Toms Run
Flood Zone: AFH
Marshall County, WV
HEC-RAS Version: RAS 6.6
Vertical Datum: NAVD88
Projection: NAD 1983 StatePlane West Virginia N FIPS 4701 (US Feet)
Terrain: 1-meter West Virginia FEMA R3 South Central (collected 2018-2019)
Land Use: 2024 NLCD
Hydrologic Method:
Duda et al., "Estimation of magnitude and frequency of floods for rural, unregulated streams in and near Virginia and West Virginia." September 8, 2025.
Additional Model Notes:
KWSE to AE tie-in
END DESCRIPTION:
DSS Export Rating Curves= 0
DSS Export Rating Curve Sorted= 0
DSS Export Volume Flow Curves= 0
DXF OffsetX= 0
DXF OffsetY= 0
DXF ScaleX= 0
DXF ScaleY= 0

--- TomsRn.p01 (plan) ---

Plan Title=Floodplain
Program Version=6.60
Short Identifier=Floodplain
Geom File=g01
Flow File=f01
Subcritical Flow
K Sum by GR= 0
Std Step Tol= 0.01
Critical Tol= 0.01
Num of Std Step Trials= 20
Max Error Tol= 0.3
Flow Tol Ratio= 0.001
Split Flow NTrial= 30
Split Flow Tol= 0.02
Split Flow Ratio= 0.02
Log Output Level= 0
Friction Slope Method= 1
Unsteady Friction Slope Method= 2
Unsteady Bridges Friction Slope Method= 1
Parabolic Critical Depth
Global Vel Dist= 0 , 0 , 0
Global Log Level= 0
CheckData=False
Encroach Param=-1 ,0,0, 0
Flow Ratio Tolerance=0.1
Flow Ratio Min Ratio=0.5
Flow Ratio Max Ratio=4
Flow Ratio Max Iterations= 10
Mapping Interval=1HOUR
Computation Time Step Use Courant=        0
Computation Time Step Use Time Series=    0
Computation Time Step Count To Double=0
Computation Time Step Max Doubling=0
Computation Time Step Max Halving=0
Computation Time Step Residence Courant=0
Run HTab= 0
Run UNet= 0
Run Sediment= 0
Run PostProcess= 0
Run WQNet= 0
Run RASMapper=-1
UNET Theta= 0
UNET Theta Warmup= 0
UNET ZTol= 0
UNET ZSATol= 0
UNET MxIter= 0
UNET Max Iter WO Improvement= 0
UNET MaxInSteps= 0
UNET DtIC= 0
UNET DtMin= 0
UNET MaxCRTS= 0
UNET WFStab= 0
UNET SFStab= 0
UNET WFX= 1
UNET SFX= 1
UNET Gravity=32.17405
UNET 1D Methodology=Finite Difference
UNET DSS MLevel= 1
UNET Pardiso=0
UNET DZMax Abort= 0
UNET Use Existing IB Tables= 0
UNET Froude Reduction=False
UNET Froude Limit= 0
UNET Froude Power= 0
UNET D1 Cores= 0
UNET WindReference=Eulerian
UNET WindDragFormulation=Hsu (1988)
UNET D2 Coriolis=0
UNET D2 Cores= 0
UNET D2 Theta= 1
UNET D2 Theta Warmup= 1
UNET D2 Z Tol= 0.01
UNET D2 Volume Tol= 0.01
UNET D2 Max Iterations= 20
UNET D2 Advanced Convergence=0
UNET D2 WS Max Tol=0.15
UNET D2 WS RMS Tol=0.002
UNET D2 WS Stall Tol=1
UNET D2 Equation= 0
UNET D2 RampUpFraction=0.1
UNET D2 TimeSlices= 1
UNET D2 Turbulence Formulation=Non-Conservative (original)
UNET D2 Eddy Viscosity=0.3
UNET D2 Transverse Eddy Viscosity=0.1
UNET D2 Smagorinsky Mixing=0
UNET D2 BCVolumeCheck=0
UNET D2 Cores=0
UNET D2 SolverType=PARDISO (Direct)
UNET D2 Minimum Iterations= 3
UNET D2 Maximum Iterations= 30
UNET D2 Restart Number= 10
UNET D2 Relaxation Coeff=1.3
UNET D2 SOR Precondition Iterations= 10
UNET D2 ILUT Maximum Fill= 8
UNET D2 ILUT Tolerance=1E-08
UNET D2 Convergence Tolerance=0.00001
PS Theta= 1
PS WS Tol= 0.01
PS Volume Tol= 0.01
PS Max Iterations= 20
PS Equation= 0
PS Advance Time Step=-1
PS Target Courant=0.9
PS Time Slices= 1
PS Iterate With 2D=0
PS Project Initial WSE from DS=-1
PS Ramp Up Initial WSE from US=-1
PS Cores=0
UNET D1D2 MaxIter= 0
UNET D1D2 ZTol=0.01
UNET D1D2 QTol=0.1
UNET D1D2 MinQTol=1
Write IC File= 0
Write IC File at Fixed DateTime=0
Write IC File at Sim End=0
Echo Input=False
Echo Parameters=False
Echo Output=False
Write Detailed= 0
HDF Write Warmup=0
HDF Write Time Slices=0
HDF Flush=0
HDF Compression= 1
HDF Chunk Size= 1
HDF Spatial Parts= 1
HDF Use Max Rows=0
HDF Fixed Rows= 1
Calibration Method= 0
Calibration Iterations= 20
Calibration Max Change=0.05
Calibration Tolerance=0.2
Calibration Maximum=1.5
Calibration Minimum=0.5
Calibration Optimization Method= 1
WQ AD Non Conservative
WQ ULTIMATE=-1
WQ Max Comp Step=1HOUR
WQ Output Interval=15MIN
WQ Output Selected Increments= 0
WQ Create Restart=0
WQ Fixed Restart=0
WQ System Summary=0
WQ Write To DSS=0
Sorting and Armoring Iterations= 10
XS Update Threshold= 0.02
Bed Roughness Predictor= 0
Processes Affected by Predictor=Sediment Only
Hydraulics Update Threshold= 0.02
Energy Slope Method= 1
Volume Change Method= 1
Sediment Retention Method= 0
Sediment TS Multiplier= 1
Warm Up Method= 0
XS Weighting Method= 0
Number of US Weighted Cross Sections= 1
Number of DS Weighted Cross Sections= 1
Upstream XS Weight=0
Main XS Weight=1
Downstream XS Weight=0
Number of DS XS's Weighted with US Boundary= 1
Upstream Boundary Weight= 1
Weight of XSs Associated with US Boundary= 0
Number of US XS's Weighted with DS Boundary= 1
Downstream Boundary Weight= 0.5
Weight of XSs Associated with DS Boundary= 0.5
Percentile Method= 0
Sediment Output Level= 3
Mass or Volume Output= 0
Output Increment Type= 1
Profile and TS Output Increment= 1
Transport Output Increment 1
XS Output Flag= 0
XS Output Increment= 10
Read HDF5 Sediment Hotstart= 0
Sediment Hotstart Type= 0
Write Gradation File= 0
Read Gradation Hotstart= 0
Write HDF5 File= 1
Write Binary Output= 1
Write DSS Sediment File= 0
DSS Sediment Output Type= 1
SV Curve= 0
Specific Gage Flag= 0
Subcell Erosion Methods= 0
Subcell Deposition Methods= 0
Advection Scheme= 1
Matrix Solver= 0
Implicit Weighting Factor= 1
Maximum Outer Loop Convergence Iterations= 5
Convergence Maximum Absolute= 0.001
Convergence RMSE= 0.0001
Grain Fractions Max Abs Error= 0.001
Max Subgrid Regions= 1
Max Subgrid Length Scale= 3.402823E+38
Initial Layer Thickness= 3
Min Layer Thickness= 0.1
Max Layer Thickness= 6
Number of Layers= 5

--- TomsRn.f01 (steady flow) ---

Flow Title=Flow
Program Version=6.60
Number of Profiles= 1
Profile Names=P100yr
River Rch & RM=TomsRn,Main,14076
     955
River Rch & RM=TomsRn,Main,11572
    1030
River Rch & RM=TomsRn,Main,10069
    1150
River Rch & RM=TomsRn,Main,8076
    1340
River Rch & RM=TomsRn,Main,4576
    1490
River Rch & RM=TomsRn,Main,1079
    1860
Boundary for River Rch & Prof#=TomsRn,Main            , 1
Up Type= 0
Dn Type= 1
Dn Known WS=751
DSS Import GetInterval= 0
DSS Import GetPeak= 0
DSS Import FillOption= 0

--- TomsRn.g01 (geometry) ---

Geom Title=Geometry
Program Version=6.60

River Reach=TomsRn          ,Main
Reach XY= 30
     1642241.393       524194.09     1641854.363      524347.965
     1640939.824       524303.06     1640482.798      523909.226
      1639931.79      523687.949     1639838.184       523369.69
     1639586.628      523351.522      1639226.53      523151.208
     1638957.155      522617.233     1638806.483      522537.166
     1638192.819      522483.652     1637965.778      522245.285
      1637580.68      522147.983     1637180.807      521738.205
     1636827.808      521582.906     1636650.366      521170.073
     1636432.701      521089.038     1636174.047      520769.077
      1635965.89      520648.125     1635728.764      520201.922
      1635498.88      520024.909      1635526.86      519884.012
     1634895.277      519483.126     1634828.131      519131.513
       1634198.8      518527.406     1634032.484      518132.718
     1633617.907      517948.562     1633853.121      517300.769
     1633834.696      516494.6511633352.57927305516235.837631098

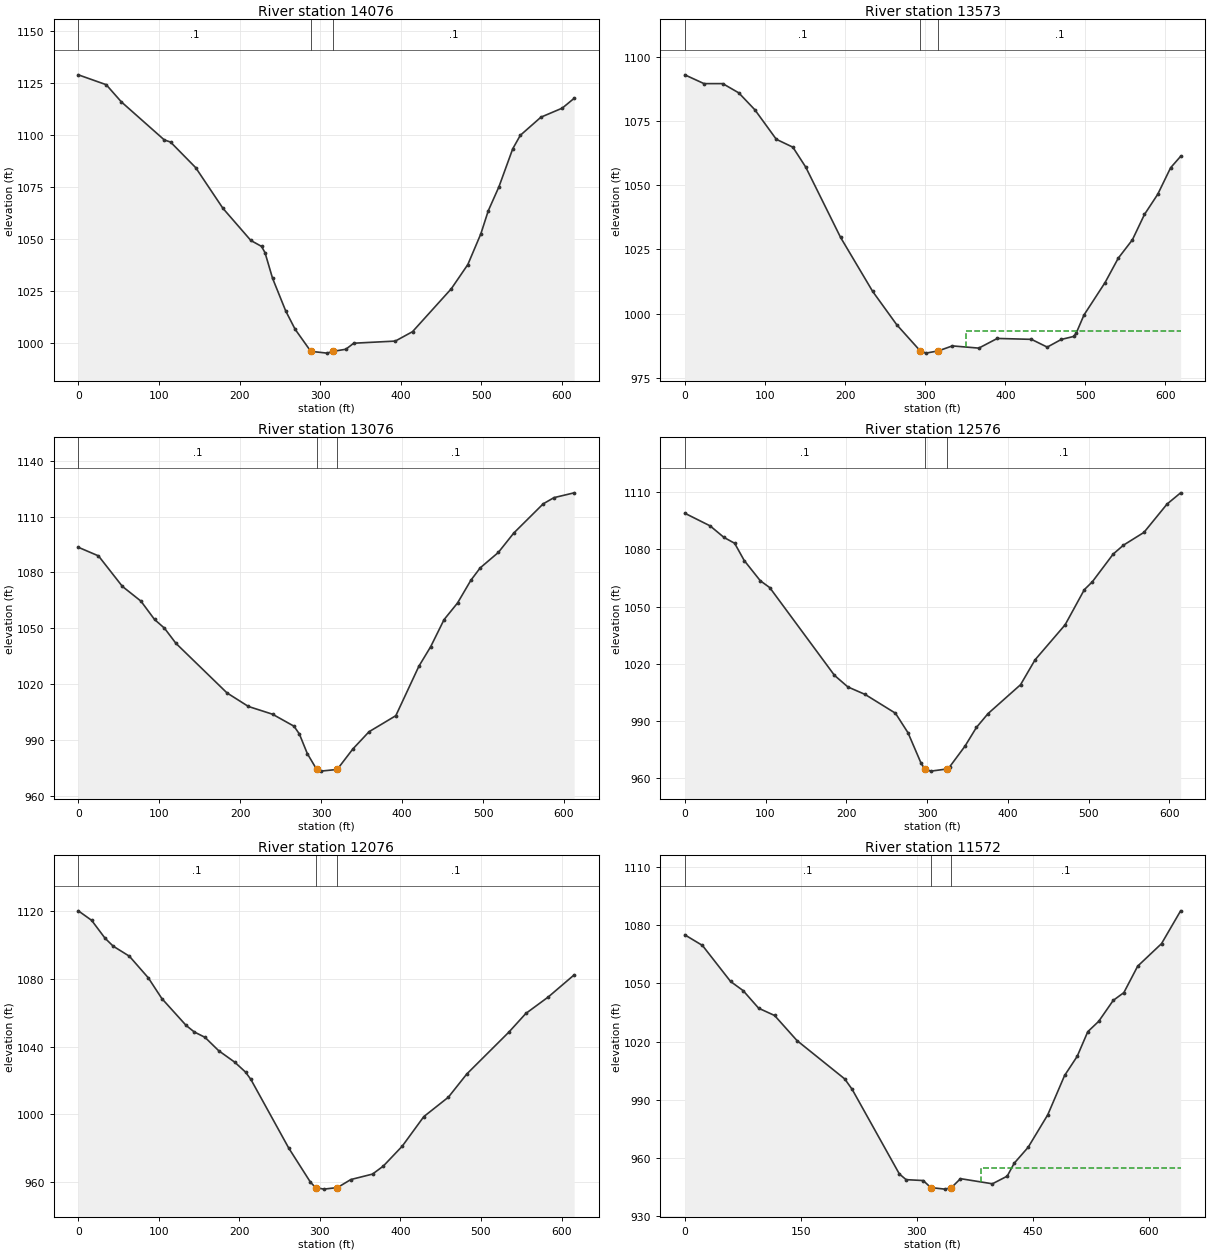
Type RM Length L Ch R = 1 ,14076   ,491.1,503.1,507
XS GIS Cut Line= 6
1642009.95469314523988.9808629011642057.15965122524072.244475886
1642104.73009413524146.4221490621642151.62796623524204.978462398
 1642320.5767753524405.8825881481642380.91523731524477.634413138
#Sta/Elev= 30
       0 1128.94    34.6 1124.19    53.4 1115.92   106.6 1097.65   114.4 1096.61
   145.6  1084.3   179.4 1064.74     214 1049.29   227.3 1046.43   231.6 1043.41
   240.9 1031.15   257.3 1015.37   268.9 1006.61  288.38995.9778   308.5  995.11
  316.24 995.978   331.8  996.97   341.7  999.88   393.2  1000.9   414.6 1005.43
   462.7 1026.07   483.2 1037.71   499.4 1052.54   508.5 1063.52   521.8 1075.12
   538.9 1093.37   548.3 1099.86   573.9 1108.58   600.3 1112.92   615.1 1117.65
#Mann= 3 ,-1,0
       0      .1       0  288.38    .045       0  316.24      .1       0
Bank Sta=288.38,316.24
XS Rating Curve= 0 ,0
Exp/Cntr(USF)=0,0
Exp/Cntr=0.3,0.1

Type RM Length L Ch R = 1 ,13573   ,495.7,496.9,494.9
XS GIS Cut Line= 6
 1641646.4324543524038.1471031461641694.98485063524289.755523816
1641707.79748905524389.3173325661641711.77057822 524466.22892414
1641715.12818305524555.9144403041641718.71282156524651.353553891
#Sta/Elev= 30
       0  1092.9      24 1089.48    47.4 1089.48    67.4 1085.88    87.5 1079.29
   114.2 1067.84   134.9 1064.76     151 1056.99   194.4  1029.7   234.5 1008.67
   264.5  995.73  293.84985.5517   300.9  984.67  316.59985.5518     334  987.48
     367  986.62     390  990.38   432.7  990.03   452.4  987.01     470     990
   485.2  991.14   488.5   992.4   498.3  999.52   524.6 1012.12     541 1021.57
   558.7 1028.74   573.8 1038.62   590.3 1046.43   606.4 1056.76   618.9  1061.2
#Mann= 3 ,-1,0
       0      .1       0  293.84    .045       0  316.59      .1       0
#XS Ineff= 2 , 0
                          351.26          993.41
Permanent Ineff=
       F       F
Bank Sta=293.84,316.59
XS Rating Curve= 0 ,0
Exp/Cntr(USF)=0,0
Exp/Cntr=0.3,0.1

Type RM Length L Ch R = 1 ,13076   ,491.2,500,509
XS GIS Cut Line= 6
1641173.50295398 524017.666501061641186.29590739524110.539674893
1641222.11571763524370.5844303971641232.34994914524444.882838234
1641244.29021397524531.5640953031641257.08283931524624.437269136
#Sta/Elev= 30
       0 1093.53    24.9  1088.9    54.4 1072.51    77.3  1064.6    94.1 1054.74
   106.4 1050.04   120.6 1041.89   183.6 1015.27   210.1 1007.97   239.9  1003.8
   266.4  997.36     273  993.22   282.9   982.6  294.47974.1172   299.5  973.21
  319.78974.1168   339.2  985.16   359.1  994.38   392.2 1003.01   420.7 1029.61
   435.3 1040.13   451.8 1054.65   468.4 1063.57   484.9  1075.8   496.4 1082.45
   518.8 1090.74   537.9 1101.18   574.3  1116.9   587.6 1120.22   612.5  1122.8
#Mann= 3 ,-1,0
       0      .1       0  294.47    .045       0  319.78      .1       0
Bank Sta=294.47,319.78
XS Rating Curve= 0 ,0
Exp/Cntr(USF)=0,0
Exp/Cntr=0.3,0.1

Type RM Length L Ch R = 1 ,12576   ,502.9,500,492.1
XS GIS Cut Line= 6
1640927.67568973523920.5318528121640877.27027872523999.578282639
1640736.13407806524220.908220559 1640697.1725418524285.014063478
1640650.57158513524359.8623389751640600.67699988524440.108241484
#Sta/Elev= 30
       0 1098.88    31.3 1092.27    48.5 1086.21    61.7 1083.15    73.6  1074.1
    93.5 1063.51   105.2 1059.92   185.3 1013.99   201.9 1007.92   223.3 1003.98
   260.8  994.16   276.4   983.9   292.2  968.31     297  964.94   304.8  963.83
  324.29964.9384   327.9  966.06   346.9   976.9   361.1  986.73   375.5  993.97
   415.7 1009.08   433.7 1022.13   470.9 1040.46   494.7 1058.87   504.5 1062.93
   530.4 1077.49   543.1 1082.15   568.5 1088.84   597.1 1103.68   613.9 1109.56
#Mann= 3 ,-1,0
       0      .1       0     297    .045       0  324.29      .1       0
Bank Sta=297,324.29
XS Rating Curve= 0 ,0
Exp/Cntr(USF)=0,0
Exp/Cntr=0.3,0.1

Type RM Length L Ch R = 1 ,12076   ,494.4,503.9,508.6
XS GIS Cut Line= 6
 1640451.9564968523573.1650934821640414.34502347523750.469856977
1640378.02947931523921.6601313951640362.46356556523995.027110636
1640340.37666747524080.4249057321640305.56079222 524170.15307273
#Sta/Elev= 30
       0  1120.3    16.5 1114.68    33.2 1104.08    43.3  1099.4    63.4 1093.45
    86.9 1080.66   103.7 1068.42   133.9  1052.5   143.9 1048.69   157.3 1045.48
   174.3 1037.57   194.2  1030.8   207.6 1024.94   214.3 1020.55   261.3  979.96
   288.1  959.91  294.54 956.642   304.9  955.71  321.82 956.641   338.4  961.38
   365.3   964.6   378.7  969.34   402.2   981.1     429  998.59   459.5 1010.08
   482.4 1023.81   534.6 1048.55   555.7  1059.6   583.5 1069.33   615.7 1082.42
#Mann= 3 ,-1,0
       0      .1       0  294.54    .045       0  321.82      .1       0
Bank Sta=294.54,321.82
XS Rating Curve= 0 ,0
Exp/Cntr(USF)=0,0
Exp/Cntr=0.3,0.1

Type RM Length L Ch R = 1 ,11572   ,511.4,497.5,484.7
XS GIS Cut Line= 6
1640181.86878239523467.8995559811640093.81482464523531.605137229
 1640015.8943768523591.1558711381639961.96961589523647.083908901
1639894.68694206523721.4836944791639710.18763913523899.297643304
#Sta/Elev= 30
       0 1075.13    22.8 1069.65    59.2 1051.02    75.4 1046.31    95.5  1037.2
   116.1 1033.44     145  1020.5   206.8 1000.64   216.4  995.24   277.4  951.53
   286.1   948.6   308.2  948.14  318.03944.4916   336.3   943.7   344.7944.4908
   356.4  949.11   397.7  946.46   416.8   950.4   425.8  957.06   443.9  965.34
   469.2   982.1     491 1002.43   507.3 1012.35     521 1025.09   535.1 1030.43
   553.9 1041.26   567.6 1045.26   585.5 1058.95   616.3 1070.58     641 1087.54
#Mann= 3 ,-1,0
       0      .1       0  318.03    .045       0   344.7      .1       0
#XS Ineff= 2 , 0
                           383.1          954.75
Permanent Ineff=
       F       F
Bank Sta=318.03,344.7
XS Rating Curve= 0 ,0
Exp/Cntr(USF)=0,0
Exp/Cntr=0.3,0.1

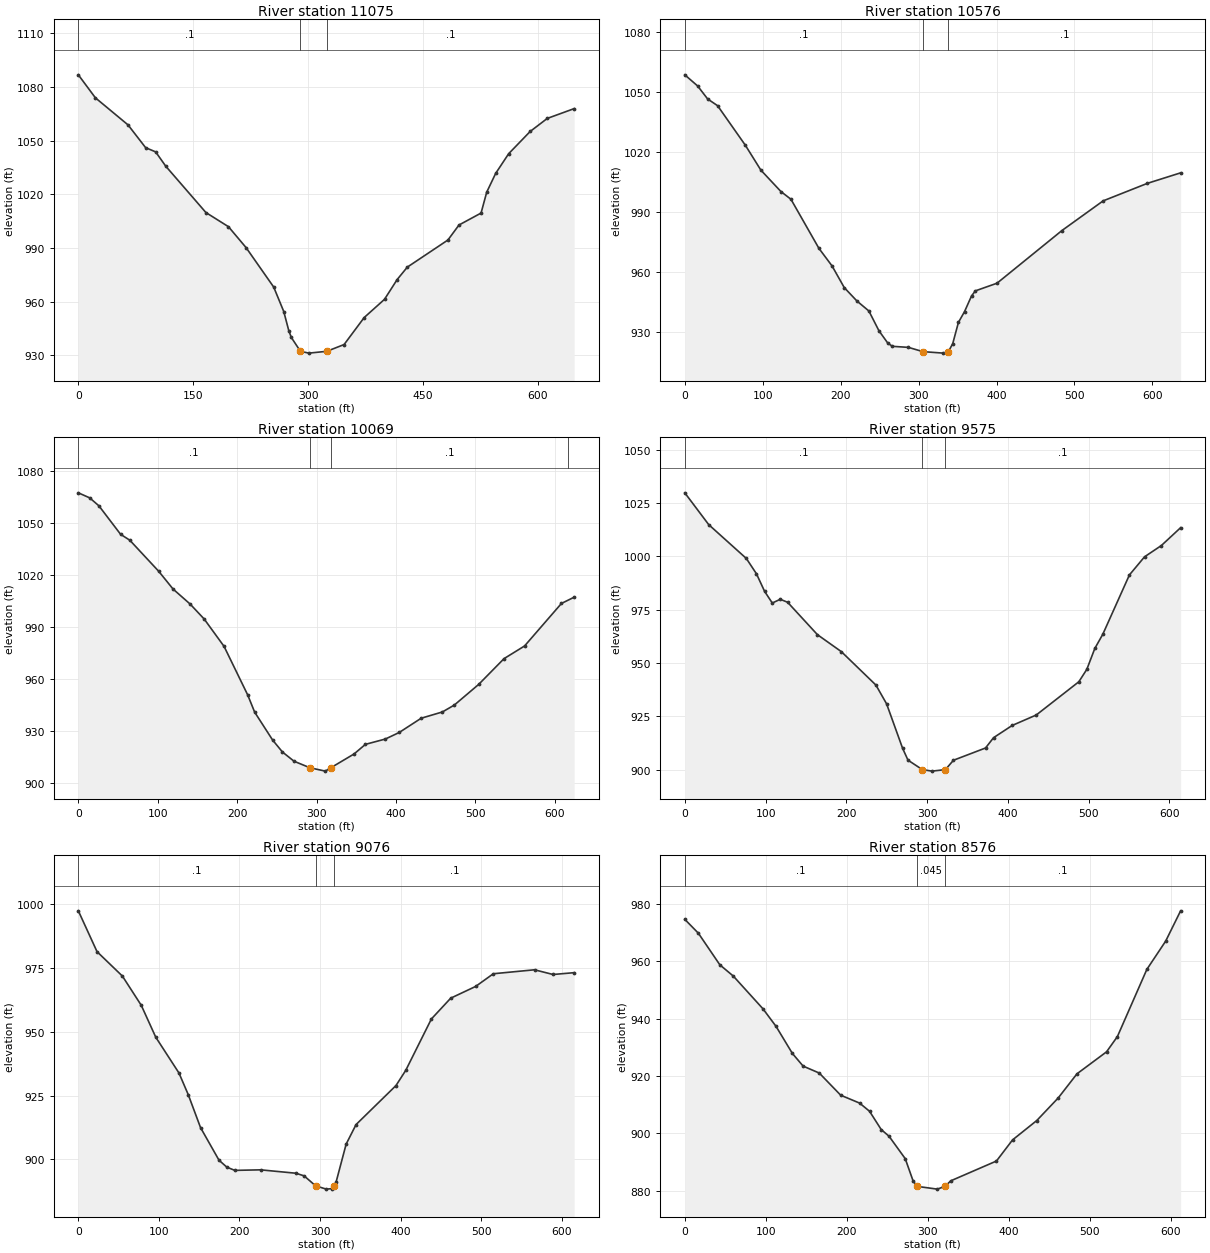
Type RM Length L Ch R = 1 ,11075   ,477.6,498.4,501.1
XS GIS Cut Line= 6
1639690.17455581523038.8216739741639688.46032038523223.119533733
1639688.67127797523400.159533978 1639678.2631623523474.547836646
 1639630.1608963523562.9869642261639565.40643264523652.485800982
#Sta/Elev= 30
       0 1086.83    22.3 1073.97    64.9 1058.84    87.9 1046.11     101 1043.75
   114.1  1035.8   166.6 1009.86   196.1 1001.92   219.1  990.24   255.2  968.16
   268.3  954.51   274.9  943.78   278.2     940  290.09932.2711   301.1  931.25
  324.58932.2724   347.1  936.05   373.4  951.16   399.9  961.33   416.4  972.37
   429.7  979.33   482.7  994.48   497.2 1002.88     526 1009.55   533.4 1021.24
   545.1 1031.74   562.1 1042.75   590.1 1055.15   612.5 1062.46   647.6 1067.94
#Mann= 3 ,-1,0
       0      .1       0  290.09    .045       0  324.58      .1       0
Bank Sta=290.09,324.58
XS Rating Curve= 0 ,0
Exp/Cntr(USF)=0,0
Exp/Cntr=0.3,0.1

Type RM Length L Ch R = 1 ,10576   ,488.1,507.6,511.7
XS GIS Cut Line= 6
1639474.03030306522929.3839007321639395.13151072522994.961197391
1639326.20120239523062.1631627231639273.64815789523123.897619307
1639223.60232621523210.4742178171639095.87128247523432.620098978
#Sta/Elev= 30
       0 1058.47    16.5 1052.91    29.3 1046.44    42.1 1043.07    77.7 1023.36
    97.6 1010.96   123.4 1000.26   136.2  996.43   172.1  971.95   188.9  963.21
   204.6  952.39   220.9  945.69   236.2  940.72   249.1  930.87   260.5  924.69
   266.4   923.1   286.9  922.58  305.65  920.45   331.9  919.71  338.24920.4505
   343.8  924.46   351.1  935.04   358.9  940.38   367.9  948.21   372.8  950.75
   400.6  954.57   483.9  980.83   536.8  995.63   593.6 1004.37   636.2  1009.6
#Mann= 3 ,-1,0
       0      .1       0  305.65    .045       0  338.24      .1       0
Bank Sta=305.65,338.24
XS Rating Curve= 0 ,0
Exp/Cntr(USF)=0,0
Exp/Cntr=0.3,0.1

Type RM Length L Ch R = 1 ,10069   ,514,493.6,480
XS GIS Cut Line= 6
1639309.27603939 522557.03129898 1639088.8450498522699.164216816
1638997.96596648 522741.059474231638927.68395481  522767.9911789
1638851.47118072522813.6465993971638780.40308139522880.925008148
#Sta/Elev= 30
       0 1067.29    14.3 1064.39    25.9 1059.81    53.2  1043.4    64.8 1039.99
   101.2 1022.09   119.3 1011.84   140.8 1003.19   158.5  994.56   183.5  978.82
   213.2   950.9     222  940.95   244.6  924.88     257  917.97   271.6  912.65
  291.67908.8776     311  906.95  317.89908.8781   347.1  916.82   361.5  922.38
   386.5  925.43     404  929.21   431.7  937.43   458.4  941.04   473.4  945.01
     504  956.88     536  971.76   561.9  979.07   608.3 1003.56   624.3 1007.16
#Mann= 4 ,-1,0
       0      .1       0  291.67    .045       0  317.89      .1       0
  616.46     .08       0
Bank Sta=291.67,317.89
XS Rating Curve= 0 ,0
Exp/Cntr(USF)=0,0
Exp/Cntr=0.3,0.1

Type RM Length L Ch R = 1 ,9575    ,484.9,498.9,505.4
XS GIS Cut Line= 6
1638606.85716864522244.0873710661638611.12750131522425.694947481
1638618.48444197522500.3801655621638632.66256322522599.482657641
1638641.07494797522674.2433348891638658.24223647 522855.16981031
#Sta/Elev= 30
       0 1029.79    29.6 1014.89    76.2  999.03    88.7  991.86    98.8  983.62
   108.3  978.16   118.2  979.91   127.3  978.51   164.2  963.33   193.8  955.38
   236.6  939.72   249.8  930.93   269.6  910.12   276.3  904.54  294.08900.1074
   306.1   899.4   322.6900.1075   332.6   904.5   372.3  910.24   382.2  915.06
   405.3   920.8   435.1   925.7   487.8  941.27   497.7   947.1   507.6   956.9
   517.5  963.55   550.4  991.32   569.1   999.8     590 1005.11   613.8 1013.46
#Mann= 3 ,-1,0
       0      .1       0  294.08    .045       0   322.6      .1       0
Bank Sta=294.08,322.6
XS Rating Curve= 0 ,0
Exp/Cntr(USF)=0,0
Exp/Cntr=0.3,0.1

Type RM Length L Ch R = 1 ,9076    ,508.2,500,491.2
XS GIS Cut Line= 6
1638326.53325422522205.1747192291638273.16229796 522285.14240706
1638227.88745414522360.5106946381638184.69233055522421.873432815
1638026.99842022522631.728656143 1637973.0539743522708.469316304
#Sta/Elev= 30
       0  997.31    23.2  981.33    54.7  971.76    78.1  960.33    96.1  947.84
   124.9  933.83   136.4  925.37   151.7  912.44   174.6  899.69   184.3  896.98
   194.2  895.71   226.3  895.92   270.1  894.59   280.3  893.55  294.38889.6786
   307.7  888.37   314.7  888.56  317.77889.6795   320.1  891.35   332.4  905.99
   344.7  913.64   394.3  928.93   406.4  934.88   438.2  954.98   462.2  963.12
   493.1  967.71   515.1  972.68   566.2  974.23   589.2  972.39   615.4   973.1
#Mann= 3 ,-1,0
       0      .1       0  294.38    .045       0  317.77      .1       0
Bank Sta=294.38,317.77
XS Rating Curve= 0 ,0
Exp/Cntr(USF)=0,0
Exp/Cntr=0.3,0.1

Type RM Length L Ch R = 1 ,8576    ,486.6,500,507.6
XS GIS Cut Line= 6
1637814.92863439521879.8312098091637800.43555313521972.457008809
1637787.54515897522059.0021113161637761.76535489522232.092972472
 1637750.7178048522306.2745826391637724.01739889 522485.54751806
#Sta/Elev= 30
       0  974.64    16.8  969.79    43.3  958.78    59.9  954.86    96.5  943.46
   112.7  937.33   132.9  927.88   146.2  923.45   166.1  921.04   192.6  913.31
   215.9  910.57   228.2  907.72   242.6  901.35   252.3     899   272.3  891.19
   282.2  883.28  287.31881.5099   311.9  880.56  321.31881.5097   328.6  883.46
     385  890.36   404.9  897.73   434.8  904.48   461.3  912.36   484.5  920.78
     521  928.44   534.4  933.76   570.8   957.2     594  967.03   612.5  977.61
#Mann= 3 ,-1,0
       0      .1       0  287.31    .045       0  321.31      .1       0
Bank Sta=287.31,321.31
XS Rating Curve= 0 ,0
Exp/Cntr(USF)=0,0
Exp/Cntr=0.3,0.1

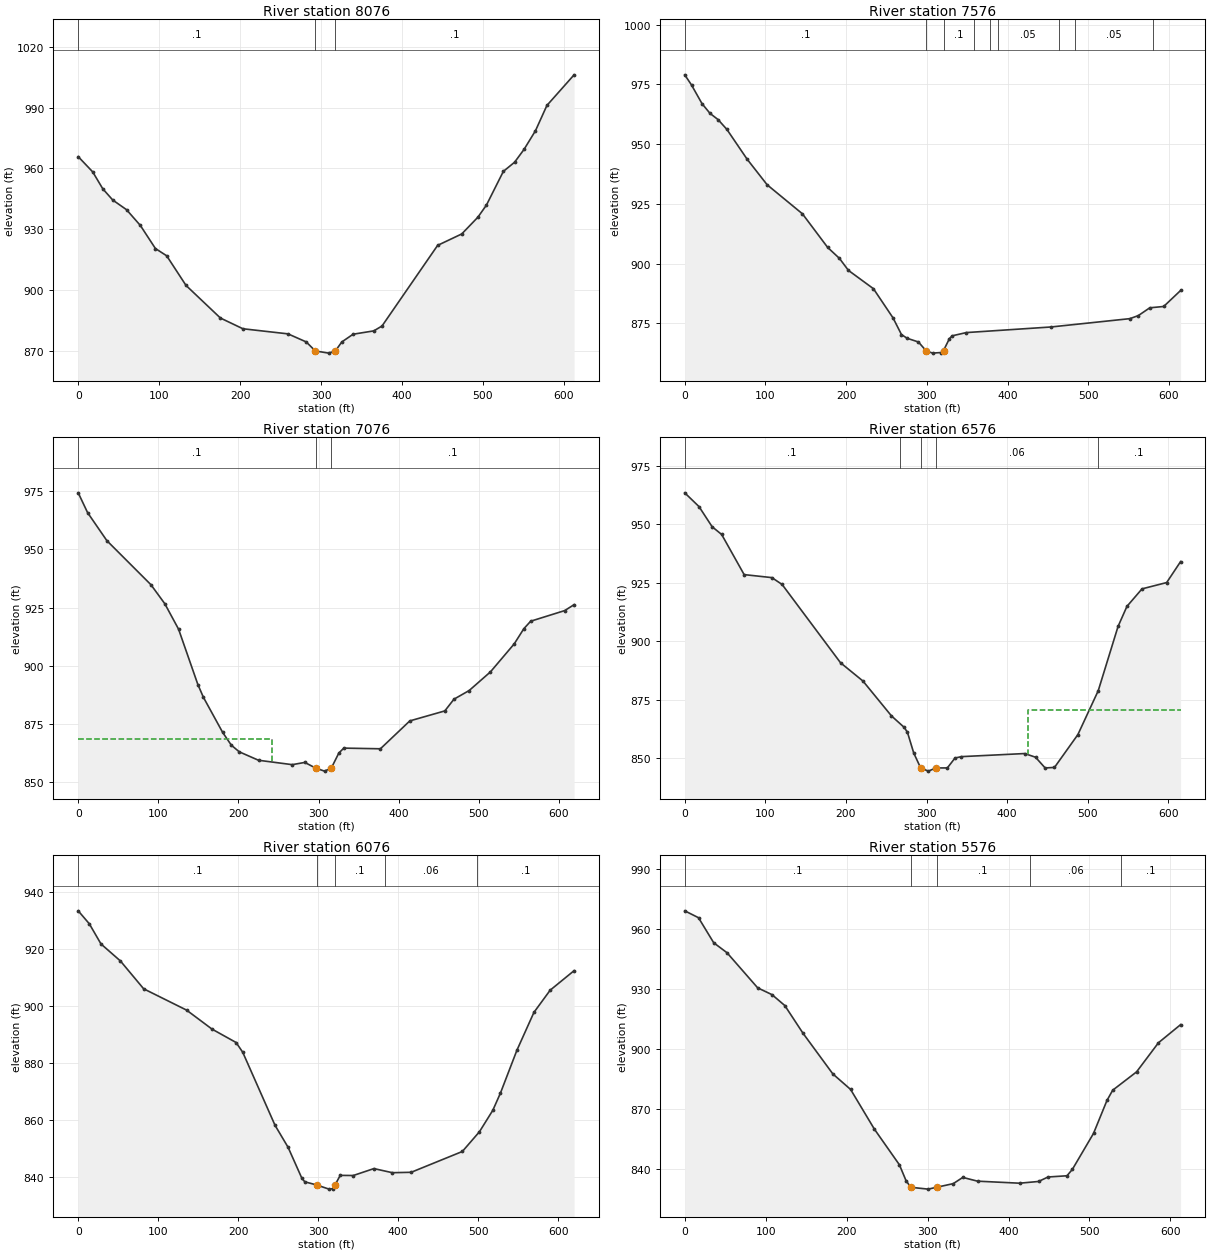
Type RM Length L Ch R = 1 ,8076    ,504.1,500,494
XS GIS Cut Line= 6
1637599.62296264 521709.841064231637471.46081738521838.005177975
1637347.71795464521961.7496811451637294.17377038522014.271557733
1637230.48328097522074.324587226 1637162.8449648522139.487842724
#Sta/Elev= 30
       0  965.81    17.9  958.29    30.4  949.91    42.7  944.38    59.7  939.62
    76.8  931.83    95.4  920.45   109.3  916.87   133.2  902.24   175.7  886.14
   203.5  880.84   259.2  878.32   281.7  874.35  292.95869.8947   309.5  868.81
  317.75 869.894   325.7  874.33   339.7  878.15   365.2  879.79   375.4  882.21
   444.1  922.01   473.9  927.65   493.8   935.9   504.4  941.89   525.3  958.53
   539.2  963.06   550.8  969.35     565  978.61   579.1  991.08   612.7  1006.2
#Mann= 3 ,-1,0
       0      .1       0  292.95    .045       0  317.75      .1       0
Bank Sta=292.95,317.75
XS Rating Curve= 0 ,0
Exp/Cntr(USF)=0,0
Exp/Cntr=0.3,0.1

Type RM Length L Ch R = 1 ,7576    ,490.5,500,509.7
XS GIS Cut Line= 6
1637082.83068913521372.9093233941637044.39178964 521460.42325598
1637017.92924413521543.9093094771636957.80075547  521708.2551094
1636901.96884614 521860.862743811636869.75729638521948.905218646
#Sta/Elev= 30
       0  979.03     8.4  974.77    21.4  966.97    31.3   962.9    41.4  960.26
    52.2   956.2    77.2  943.77   102.1  933.01   145.8  920.87   177.1  906.79
   191.7   902.2   202.8  897.19   233.8  889.52   258.1  877.29   268.5  870.35
   275.5  868.78   289.5  867.23  298.86863.6258     307  862.56   317.4  862.81
  320.63863.6254   327.9  868.61   331.4  869.81   348.9  871.16   453.7   873.5
   551.5  876.99     562  878.27   576.2  881.53   593.4  882.08   614.4  888.78
#Mann= 9 ,-1,0
       0      .1       0  298.86    .045       0  320.63      .1       0
  358.16     .05       0  378.16      .1       0  388.16     .05       0
  463.16     .03       0  483.16     .05       0  580.66      .1       0
Bank Sta=298.86,320.63
XS Rating Curve= 0 ,0
Exp/Cntr(USF)=0,0
Exp/Cntr=0.3,0.1

Type RM Length L Ch R = 1 ,7076    ,504.9,500,492.3
XS GIS Cut Line= 6
1636972.52940056521195.0340229721636882.65458031521223.291840479
1636799.36373639521250.1208550631636560.59748164521324.220116317
1636483.49297705 521369.060577811636407.69555648521431.401988566
#Sta/Elev= 30
       0  974.31    11.7  965.81    35.8  953.75    90.8  934.83   108.1  926.67
   125.3  915.73   149.4  891.94   156.3  886.46   180.4  871.34   191.2  865.88
   201.1  863.03   225.1  859.41   267.2  857.52   282.9  858.48  296.41856.0515
   307.5  854.74  316.01856.0526   325.4  862.52   331.6  864.63   377.3  864.34
     414  876.32   457.7  880.61   469.1  885.64   488.1  889.37   514.7  897.39
   544.4  909.44   556.4  915.95   564.9  919.15   607.4  923.72   619.1  926.26
#Mann= 3 ,-1,0
       0      .1       0  296.41    .045       0  316.01      .1       0
#XS Ineff= 2 , 0
          242.09  868.35
Permanent Ineff=
       F       F
Bank Sta=296.41,316.01
XS Rating Curve= 0 ,0
Exp/Cntr(USF)=0,0
Exp/Cntr=0.3,0.1

Type RM Length L Ch R = 1 ,6576    ,494.2,500,501
XS GIS Cut Line= 6
1636514.05361147520738.5851327331636455.70530297520812.231967062
1636403.48263839520882.578939229 1636306.4116383 521028.18855615
1636255.24146505521083.9013712261636127.21908331521214.596647888
#Sta/Elev= 30
       0  963.47    17.7  957.59      34  948.98    45.8  945.68    73.7  928.53
   108.1  927.25   120.8  924.32   193.3  890.87   221.1  883.07   256.5  868.16
   272.3  863.26   276.3  861.16   284.1  852.32   292.7  845.93   302.2  844.58
   311.7  845.94   325.8  845.95   335.3  850.18   343.3  850.77   421.7  852.09
   435.2  850.53   447.1  845.94   458.7  846.16   487.7  860.16     513  878.94
   537.6  906.41   548.6  914.96   567.3  922.44   597.9  925.14   615.2  934.11
#Mann= 5 ,-1,0
       0      .1       0  266.57     .06       0   292.7    .045       0
   311.7     .06       0  512.22      .1       0
#XS Ineff= 2 , 0
                          426.06          870.81
Permanent Ineff=
       F       F
Bank Sta=292.7,311.7
XS Rating Curve= 0 ,0
Exp/Cntr(USF)=0,0
Exp/Cntr=0.3,0.1

Type RM Length L Ch R = 1 ,6076    ,498,500,500.7
XS GIS Cut Line= 6
1636199.80653656520442.6428112241636133.13737856520515.149227887
1636073.15619931520581.6700922251636018.81903763520634.308766484
1635941.99635664 520698.326354981635745.13946688520862.373599067
#Sta/Elev= 30
       0  933.56    13.9     929    28.5  921.92    52.8  915.95    81.8  906.19
   135.5   898.7   167.2  892.05   197.4  887.33   205.7  883.91   246.1  858.25
   262.4  850.54   279.6  839.69   283.3  838.42  298.22 837.306   313.6  835.85
   318.2  836.03   321.1837.3082   327.6  840.68   343.9  840.63   369.7  843.06
   392.8  841.62   416.3  841.76   480.3  849.07   501.7  856.01   518.4  863.54
   527.9  869.56   548.6  884.67   569.8  897.91   590.1   905.7     620  912.55
#Mann= 5 ,-1,0
       0      .1       0  298.22    .045       0   321.1      .1       0
  383.72     .06       0  498.72      .1       0
Bank Sta=298.22,321.1
XS Rating Curve= 0 ,0
Exp/Cntr(USF)=0,0
Exp/Cntr=0.3,0.1

Type RM Length L Ch R = 1 ,5576    ,494.1,502.3,500.7
XS GIS Cut Line= 6
1636000.57038647520059.0553238091635923.07283805520111.877396643
1635850.57265498 520160.91470015 1635788.0681868520202.382464975
1635567.07486239520344.044583231 1635488.8640608 520395.75871864
#Sta/Elev= 30
       0  969.26      17  965.81    35.8  953.25    52.2  948.27    90.1  930.67
   107.8  927.26   123.6  921.81   146.1  907.92     183  887.52   204.9  879.76
   234.2  859.92   265.2     842   273.4  834.05  279.28830.7286   300.7  829.81
  311.02830.7277   331.7  832.56   343.5  835.68   361.7   833.8   413.7  832.78
   437.1  833.65   448.8  835.89   472.2   836.5   478.9  839.73     505  857.73
   521.6  874.24   528.7  879.38   558.2  888.57   585.2  903.15   612.6  912.24
#Mann= 5 ,-1,0
       0      .1       0  279.28    .045       0  311.02      .1       0
  426.32     .06       0  538.82      .1       0
Bank Sta=279.28,311.02
XS Rating Curve= 0 ,0
Exp/Cntr(USF)=0,0
Exp/Cntr=0.3,0.1

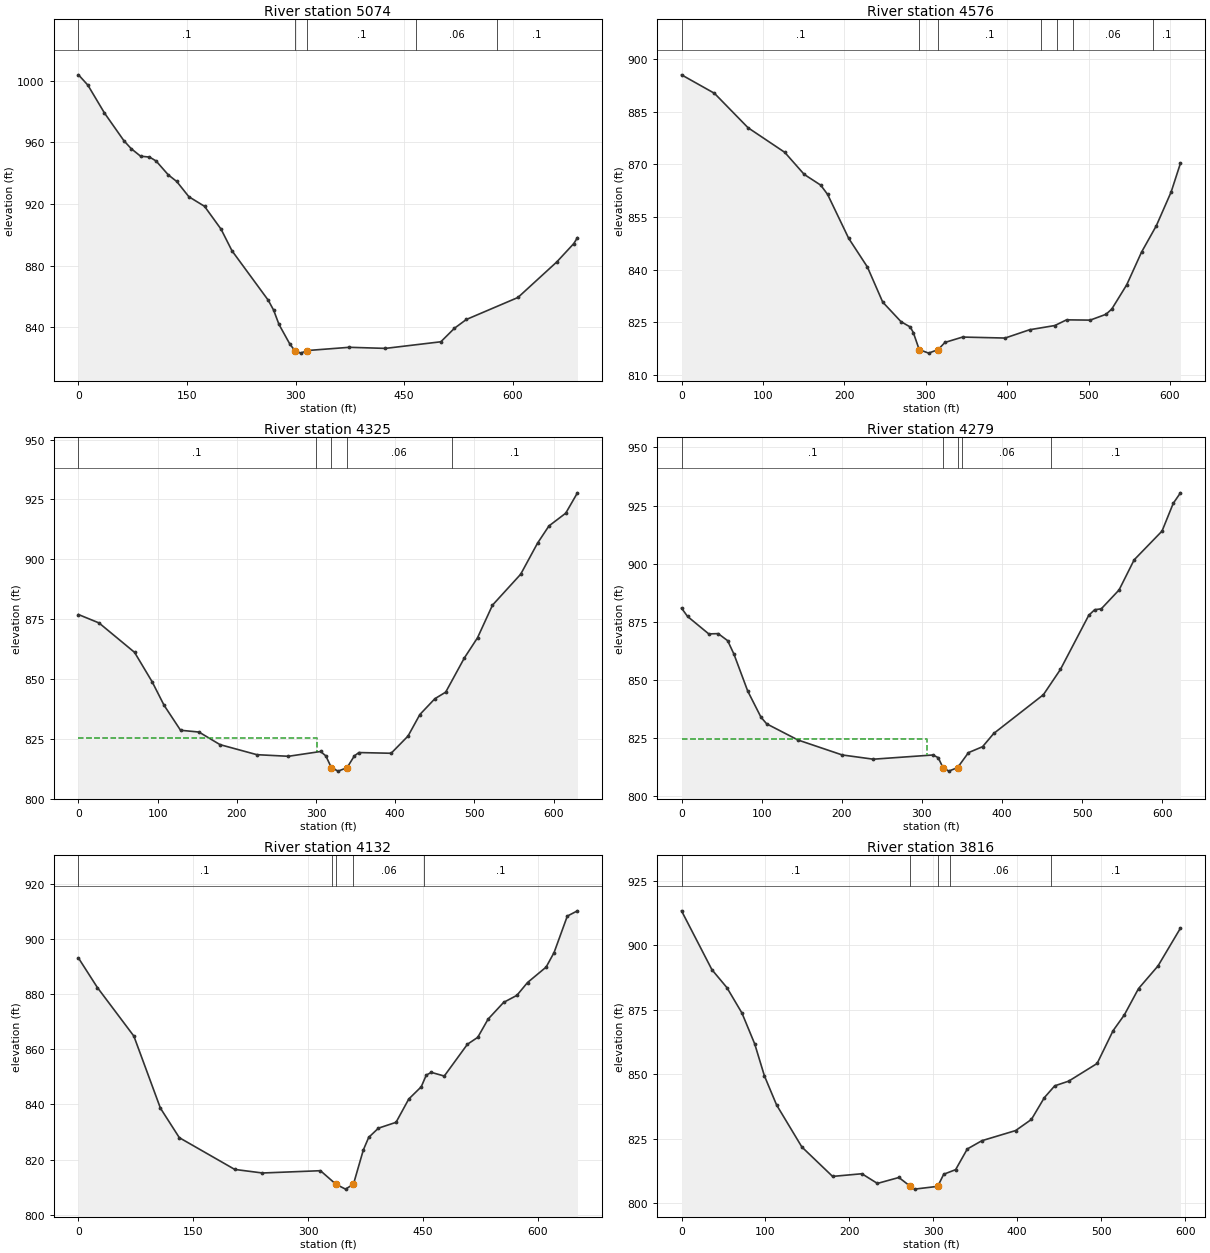
Type RM Length L Ch R = 1 ,5074    ,499.7,497.7,489.9
XS GIS Cut Line= 6
1635791.27159247519729.4195001421635572.12800188519862.235507473
1635466.56062771 519919.873843641635379.41021147519971.611272976
1635290.43794847520029.2112233941635203.05820197520088.260317892
#Sta/Elev= 30
       0  1003.7    12.9  997.05    35.9  978.94    62.8  960.96    72.8  955.85
    85.8  950.95    98.1  950.39   107.2  947.86   124.1  938.84   135.7  934.58
   152.5  924.68   174.1  918.48     197  903.62     212  889.69   262.1  857.62
   269.6  851.15     277  841.89     292  829.17   298.8  824.98     307   823.3
  316.12824.9807   374.2  827.08     424  826.37   500.6  830.66   519.4  839.43
   535.8   845.1   607.1  859.37   660.8  882.43   684.2  894.29   689.3  898.15
#Mann= 5 ,-1,0
       0      .1       0   298.8    .045       0  316.12      .1       0
  466.53     .06       0  577.88      .1       0
Bank Sta=298.8,316.12
XS Rating Curve= 0 ,0
Exp/Cntr(USF)=0,0
Exp/Cntr=0.3,0.1

Type RM Length L Ch R = 1 ,4576    ,250.2,250.8,250.1
XS GIS Cut Line= 6
1635282.92221548519367.7259978061635157.91688806519591.417151481
 1635109.1345053 519678.711596311635072.54698005519744.181937814
1635029.86038564519820.5633467291634989.23152989519905.357140392
#Sta/Elev= 30
       0  895.45    40.4   890.2    81.7   880.4   126.8   873.4   150.7  867.12
   170.9  864.08   179.4  861.44   205.3  848.94   228.3  840.78   247.1   830.8
   269.6  825.22   280.9  823.72   284.7  822.13  291.92817.2797   303.5  816.28
  315.15 817.282   323.5  819.32   345.2  820.85   397.4  820.57   427.5  822.93
   458.5  824.13   472.9  825.75   501.9  825.67   521.4  827.33   528.5  828.84
   546.8  835.72     565  845.02   583.2  852.54   601.4  862.16   612.8  870.32
#Mann= 7 ,-1,0
       0      .1       0  291.92    .045       0  315.15      .1       0
  441.25     .06       0  461.25      .1       0  481.25     .06       0
  578.75      .1       0
Bank Sta=291.92,315.15
XS Rating Curve= 0 ,0
Exp/Cntr(USF)=0,0
Exp/Cntr=0.3,0.1

Type RM Length L Ch R = 1 ,4325    ,45.1,46.4,45.9
XS GIS Cut Line= 5
1635219.02680731519391.2674085381635117.91219576519446.420833018
1634945.55774426519475.1465749341634906.49073525519546.386414887
1634667.49256251519646.351996756
#Sta/Elev= 30
       0  876.91    25.9  873.41    70.8  861.13      93  848.85   108.1  839.01
   128.9  828.58   152.2  827.83   178.8  822.57   225.3  818.38   265.2  817.71
   305.8  819.71   312.4  817.88   319.4812.9618     328  811.51  339.21812.9651
   348.5  817.89   354.2  819.27   394.9  818.97   416.2  826.15   431.2  835.16
   450.1  841.75   463.8   844.5   487.4   858.8     504  867.21   522.9  880.84
   558.5  893.75   579.8  906.73   594.2  913.92   615.4  919.24   630.2  927.75
#Mann= 5 ,-1,0
       0      .1       0  299.91     .06       0   319.4    .045       0
  339.21     .06       0  471.16      .1       0
#XS Ineff= 2 , 0
          301.23  825.22
Permanent Ineff=
       F       F
Bank Sta=319.4,339.21
XS Rating Curve= 0 ,0
Exp/Cntr(USF)=0,0
Exp/Cntr=0.3,0.1

Type RM Length L Ch R = 1 ,4279    ,133.1,147.2,154.4
XS GIS Cut Line= 5
1635175.36367959519320.0275685851635083.44130546519380.926141448
1634921.42812105519430.3344175441634875.46693399519509.617465234
1634639.91585027 519596.94372066
#Sta/Elev= 30
       0  880.92     7.6  877.32      34  869.83    45.8  869.95    57.6  866.91
    65.4  861.14    82.6  845.27    99.2  833.99   106.3  831.16   145.3  824.23
   200.5   817.8   239.3  815.98   313.8  817.79   320.2  816.64  326.24 812.377
   333.5  810.85  344.44 812.378     358   818.8   375.6  821.35   389.5  827.03
   451.5   843.7   472.7  854.54   508.1  877.84   515.5  880.23   523.7  880.61
   545.9  888.73   564.7  901.66   599.5  914.03   613.5  925.96   622.5  930.47
#Mann= 5 ,-1,0
       0      .1       0  326.24    .045       0  344.44      .1       0
  349.64     .06       0  461.29      .1       0
#XS Ineff= 2 , 0
          306.79  824.64
Permanent Ineff=
       F       F
Bank Sta=326.24,344.44
XS Rating Curve= 0 ,0
Exp/Cntr(USF)=0,0
Exp/Cntr=0.3,0.1

Type RM Length L Ch R = 1 ,4132    ,327.1,315.3,305.1
XS GIS Cut Line= 6
1635185.68312112519299.2892514551635084.86221637 519361.40632231
1634823.15506261 519340.979197811634747.37109345519335.786950985
1634656.85290178519356.3423560651634560.41871145519389.191699812
#Sta/Elev= 30
       0  893.09    24.7  882.39    72.3   864.8     107  838.67   131.7  827.96
   204.1  816.45   240.3  815.16     316  815.99  336.23811.0804   348.7  809.31
  359.06811.0809     372  823.52     379  828.08   391.7  831.41   414.7  833.53
   431.3  841.97   447.6  846.41   454.2  850.65   460.8  851.64   477.7  850.31
   507.9  861.83   521.4  864.34   534.9  870.94   555.2  877.01   572.5  879.56
   586.4  884.21   610.7  889.81   621.1  895.09   638.4  908.31   651.6  910.21
#Mann= 5 ,-1,0
       0      .1       0  330.92     .06       0  336.23    .045       0
  359.06     .06       0  450.93      .1       0
Bank Sta=336.23,359.06
XS Rating Curve= 0 ,0
Exp/Cntr(USF)=0,0
Exp/Cntr=0.3,0.1

Type RM Length L Ch R = 1 ,3816    ,330.9,332.3,324.7
XS GIS Cut Line= 2
 1634963.6900315518883.1677464581634527.09027782519286.667879825
#Sta/Elev= 30
       0  913.39    36.2  890.59    54.1  883.62      72  873.78    87.2  861.82
    98.8   849.4   113.3  838.14   143.4  821.86     180  810.46   214.9  811.49
   233.4  807.74     259  810.04  272.68806.6036   277.6  805.53  305.25806.6005
   312.4  811.29   326.6  813.08   340.5  821.09   357.9   824.3   398.1  828.23
   416.9  832.54   432.3  840.98   444.7  845.57   461.3  847.38   495.2  854.23
   514.2  866.94   527.6  873.04   544.5  883.24   567.7  892.02   594.5  906.69
#Mann= 5 ,-1,0
       0      .1       0  272.68    .045       0  305.25      .1       0
     320     .06       0     440      .1       0
Bank Sta=272.68,305.25
XS Rating Curve= 0 ,0
Exp/Cntr(USF)=0,0
Exp/Cntr=0.3,0.1

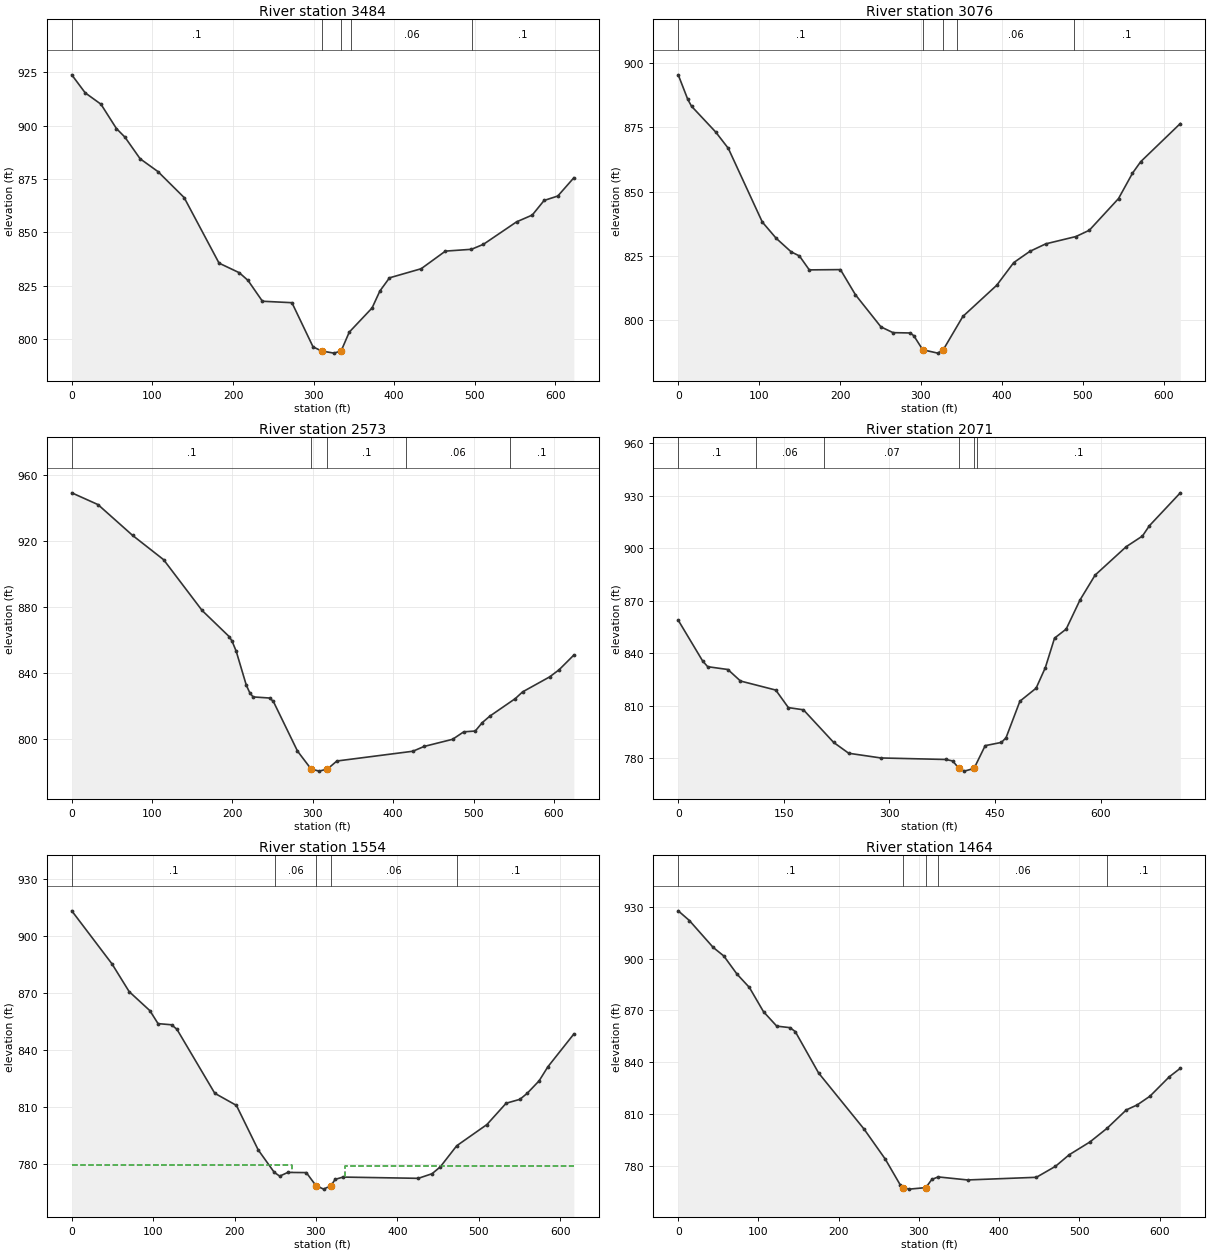
Type RM Length L Ch R = 1 ,3484    ,406.1,407.9,410.5
XS GIS Cut Line= 6
1634693.16529493518551.9104464861634646.30482435518633.556280574
1634579.43881633518781.6695014151634530.74435992518869.992815575
1634417.91748584518995.4335095791634346.50555518519060.372356078
#Sta/Elev= 30
       0  923.86    16.7   915.4    36.2  910.09    55.4  898.67    65.9  894.67
    84.8  884.51   106.9  878.51   139.4  866.33   182.7  835.59   207.8   831.1
   218.6   827.5   236.5  817.73   273.1  817.05   299.3  796.34   309.9 794.424
   325.2  793.41  334.12794.4242   344.2  803.25   372.5  814.57   382.2  822.53
   394.1   828.7   433.4  832.97   463.5  841.23   495.8  842.08   510.7  844.43
   551.7  854.93   571.2  858.13   585.9  864.97   602.9  867.05   622.8   875.6
#Mann= 5 ,-1,0
       0      .1       0   309.9    .045       0  334.12      .1       0
  346.65     .06       0  495.96      .1       0
Bank Sta=309.9,334.12
XS Rating Curve= 0 ,0
Exp/Cntr(USF)=0,0
Exp/Cntr=0.3,0.1

Type RM Length L Ch R = 1 ,3076    ,499.5,503,502.6
XS GIS Cut Line= 6
 1634477.7400988 518369.829699651634393.94138189518422.309581563
1634321.36245881518476.2625576411634271.81596997 518532.61874415
 1634208.2347323518609.8033010661634045.33381139518807.609335899
#Sta/Elev= 30
       0  895.47    11.8   885.9    16.4  883.25    46.4  873.16    61.9  866.83
   103.9  838.14   121.1   831.8   139.6  826.52   149.8  824.93     162   819.5
   200.5  819.61   219.1  809.79   250.6  797.29   265.5  795.06   286.8  794.93
   291.2  793.85  302.21 788.392   320.8  787.08  327.57788.3926   351.8  801.36
   393.7  813.52   414.7  822.34   434.6  826.71   454.3  829.64   491.6  832.49
   508.1  834.93   544.2  847.27   561.5  857.16   571.6  861.63   620.6   876.5
#Mann= 5 ,-1,0
       0      .1       0  302.21    .045       0  327.57      .1       0
  344.35     .06       0  489.35      .1       0
Bank Sta=302.21,327.57
XS Rating Curve= 0 ,0
Exp/Cntr(USF)=0,0
Exp/Cntr=0.3,0.1

Type RM Length L Ch R = 1 ,2573    ,495.7,502.5,511.3
XS GIS Cut Line= 6
1634220.96370947517891.3168771421634061.17564322518091.646528974
1633994.11573797518166.0719050621633937.93277948518217.529151231
1633874.19143714518284.3735057261633805.31755914 518356.63451606
#Sta/Elev= 30
       0  949.24    32.6  942.11    75.8  923.37   114.3  908.67   162.2  877.86
   196.2  861.86   199.6  859.08   204.6  853.18   217.2  832.51   221.4  828.04
   225.6  825.41   246.3  824.73   250.9  822.64   280.9  792.54  297.83781.6635
   307.9  780.38  318.17781.6616   329.9  786.52   424.5  792.45   438.6  795.38
   473.9  799.69   487.8  804.22   502.1  804.71   510.8  809.79   520.2  813.73
     552  824.41     561  828.46   594.6  837.54   606.4  841.86   624.8  850.81
#Mann= 5 ,-1,0
       0      .1       0  297.83    .045       0  318.17      .1       0
  416.43     .06       0  544.98      .1       0
Bank Sta=297.83,318.17
XS Rating Curve= 0 ,0
Exp/Cntr(USF)=0,0
Exp/Cntr=0.3,0.1

Type RM Length L Ch R = 1 ,2071    ,509.4,516.7,522.3
XS GIS Cut Line= 6
1633984.50978605517758.805003062 1633868.6350178517809.909231558
1633752.94036731517859.7027671491633660.56948905517901.342447639
1633558.08019271517909.5399378091633301.94783098517901.777486146
#Sta/Elev= 30
       0   858.8    34.6  835.56    41.8  832.25    70.5  830.64    88.4  824.06
   138.5  818.89   156.4  808.87   177.8  807.61   220.7  788.98   242.1  782.78
   287.7   780.1     380  779.22   389.8  778.39  398.72774.1032   406.3  772.57
  420.07774.1025   435.9  787.13     459  788.99   465.5  791.64   485.2  812.52
   508.2  819.96   521.3  831.69   534.4  848.58   550.9  853.73   570.6  870.41
     592  884.58   636.2  900.83   659.2   906.9     669  912.75     713   931.6
#Mann= 6 ,-1,0
       0      .1       0     110     .06       0  206.64     .07       0
  398.72    .045       0  420.07     .07       0  423.92      .1       0
Bank Sta=398.72,420.07
XS Rating Curve= 0 ,0
Exp/Cntr(USF)=0,0
Exp/Cntr=0.3,0.1

Type RM Length L Ch R = 1 ,1554    ,88.8,90.4,86.1
XS GIS Cut Line= 4
1634073.88658943517487.1280260391633794.36642152517442.643028343
1633744.17761441517408.8257937481633478.24423273517345.792712048
#Sta/Elev= 30
       0  913.33    49.5  885.33    70.5  870.78      96  860.73     106  853.91
   122.6   853.3   129.2  850.93   175.7  817.22   202.3  810.83   229.1  787.37
   248.8  775.56   255.5  773.56   265.4  775.52   288.2  775.43  300.03768.5594
   309.5  766.72   318.5 768.558   323.6  771.86   333.3  773.07   425.8  772.41
   442.7  774.84   452.8  778.45     473  789.57   510.1  800.74   533.7  811.97
   550.6  814.02   559.4  817.12   574.2  823.75     585  831.18   616.9  848.44
#Mann= 5 ,-1,0
       0      .1       0     250     .06       0  300.03    .045       0
   318.5     .06       0  473.56      .1       0
#XS Ineff= 2 , 0
           270.4  779.66   335.6          778.99
Permanent Ineff=
       F       F
Bank Sta=300.03,318.5
XS Rating Curve= 0 ,0
Exp/Cntr(USF)=0,0
Exp/Cntr=0.3,0.1

Type RM Length L Ch R = 1 ,1464    ,386.9,384.2,371.1
XS GIS Cut Line= 4
1634107.71890229517406.8696417181633845.19931375 517378.44074676
1633794.53826832517344.6235121651633504.04849422517266.006566042
#Sta/Elev= 30
       0  927.66    13.9  922.04    43.6  906.43    56.8  901.49    73.3  890.95
    88.7  883.24   106.3  869.17   122.8  860.82   139.3  859.93   145.9  857.65
     175  833.64   231.7   801.1   258.1  783.72   276.6   768.9   280.1767.1914
     288  766.32  308.59 767.194   316.1  771.91     324   773.4   360.7  771.64
   446.5  773.18   470.3  779.55   487.3  786.22   513.2  793.66   534.6   801.6
   558.6  812.25   572.2  815.15   588.1  820.21   612.1  831.42   625.9  836.37
#Mann= 5 ,-1,0
       0      .1       0   280.1    .045       0  308.59      .1       0
  324.05     .06       0  534.97      .1       0
Bank Sta=280.1,308.59
XS Rating Curve= 0 ,0
Exp/Cntr(USF)=0,0
Exp/Cntr=0.3,0.1