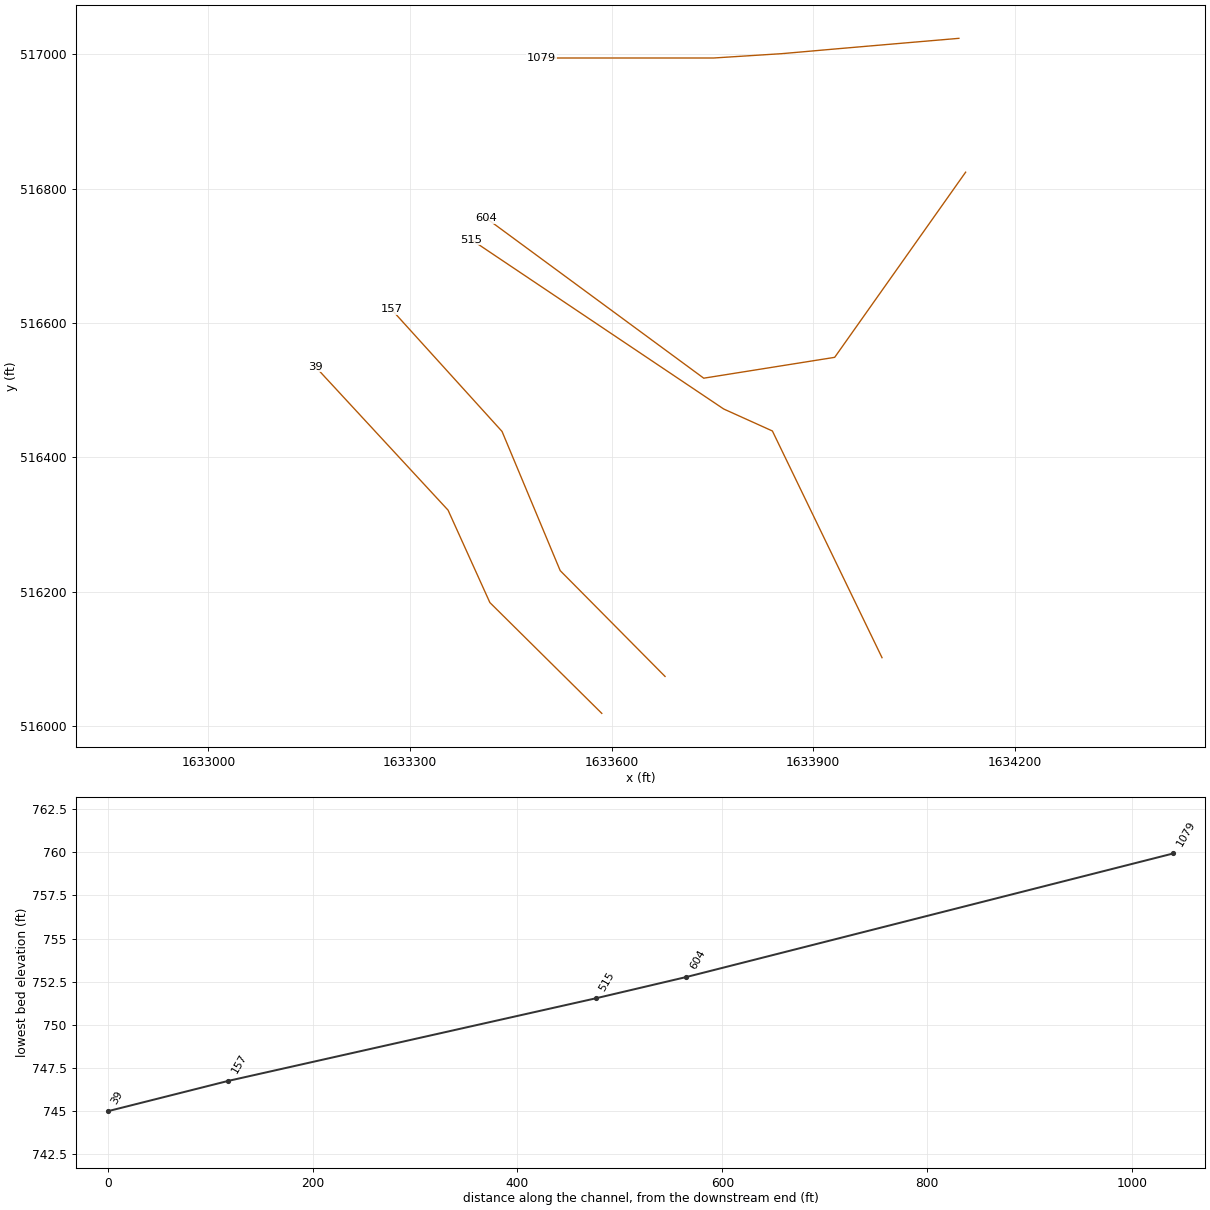
HEC-RAS study TomsRn.prj: TomsRn

--- TomsRn.g01 (geometry) --- (continued)

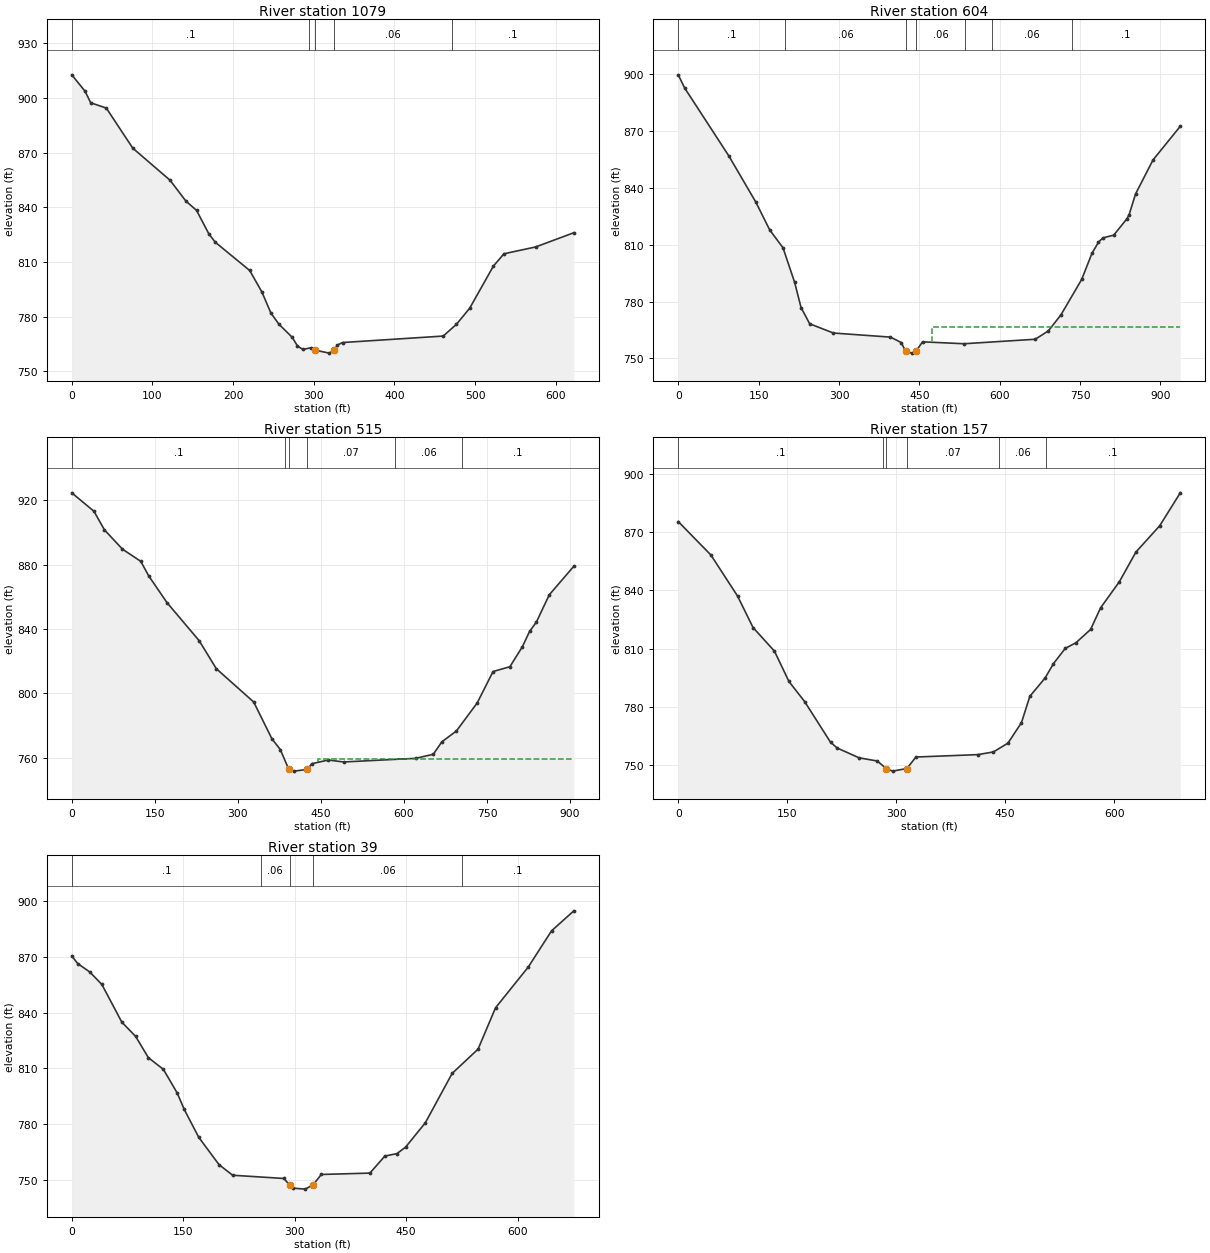
Type RM Length L Ch R = 1 ,1079    ,473.1,475.4,475.2
XS GIS Cut Line= 6
1634116.83498073517023.6050298961634021.47493522517015.440348059
1633931.38718888517007.6651011411633853.13603306517000.784865558
1633751.79207563516994.3386842311633495.54193197516994.338684231
#Sta/Elev= 30
       0  912.75    16.4  903.79    23.5  897.39    42.8   894.5    75.7  872.46
   121.8   854.9   141.5  843.43   154.7  838.33   170.1  825.31   178.1  820.78
   220.6  805.32   235.7  793.54   246.9  781.96   256.8  775.84   273.3  768.65
   279.8  763.91   286.4  761.96   296.3  762.86  301.94761.5422   319.3  759.94
  325.73761.5406   329.1  764.31   335.7  765.76   460.5  769.31   476.9  775.74
   493.3  784.56   522.8  807.77   535.9   814.5   575.3  818.25   622.5  826.06
#Mann= 5 ,-1,0
       0      .1       0  294.68     .06       0  301.94    .045       0
  325.73     .06       0  471.23      .1       0
Bank Sta=301.94,325.73
XS Rating Curve= 0 ,0
Exp/Cntr(USF)=0,0
Exp/Cntr=0.3,0.1

Type RM Length L Ch R = 1 ,604     ,93.9,88.7,81.8
XS GIS Cut Line= 4
1634126.88672087516824.4286795331633932.01736948 516548.88093425
1633737.14801809516517.8507827551633413.19323647516756.162346243
#Sta/Elev= 30
       0  899.81    12.2  892.75    94.4  856.98   144.9  832.51   170.7  817.87
   195.6  808.38   217.2  790.19   229.2  776.87   245.3  768.28   289.5  763.39
   396.1  761.23   416.1  758.37  424.36  753.76     436  752.77   443.8  753.77
   455.9  758.74   533.4  757.73   666.2   760.1   690.6  764.47   714.2  772.97
   752.9  791.69   772.1  805.49   784.3  811.39   792.4  813.64   812.8  815.12
   837.3  823.74   841.4  825.87   853.5  836.89   886.1  854.86     937  872.63
#Mann= 7 ,-1,0
       0      .1       0     200     .06       0  424.36    .045       0
   443.8     .06       0  534.82     .07       0  584.82     .06       0
  734.82      .1       0
#XS Ineff= 2 , 0
                          472.92          766.59
Permanent Ineff=
       F       F
Bank Sta=424.36,443.8
XS Rating Curve= 0 ,0
Exp/Cntr(USF)=0,0
Exp/Cntr=0.3,0.1

Type RM Length L Ch R = 1 ,515     ,366,358.7,342.6
XS GIS Cut Line= 4
      1634002.46       516101.911633839.30356719516439.310583451
1633766.86986144516472.000846874     1633391.048      516724.159
#Sta/Elev= 30
       0  924.74      40  913.28      59   901.7    91.6  889.66   124.6  882.11
   139.1  872.99   171.9  856.43   230.2  832.67   261.1  815.27   328.6  794.55
   361.4  771.72   376.6  764.95  392.07  752.57   401.4  751.53   425.3  752.57
   433.6  756.16   463.4  758.45     491  757.23   621.4   759.5     653  762.03
   668.4  769.76   694.7  776.52   732.1   793.9   760.9  813.52   791.3  816.51
   813.8  828.93   826.9   838.5   839.2  844.34   862.4  861.27   906.8  879.06
#Mann= 6 ,-1,0
       0      .1       0  384.78     .07       0  392.07    .045       0
   425.3     .07       0  584.25     .06       0  704.25      .1       0
#XS Ineff= 2 , 0
                          444.56          759.15
Permanent Ineff=
       F       F
Bank Sta=392.07,425.3
XS Rating Curve= 0 ,0
Exp/Cntr=0.3,0.1

Type RM Length L Ch R = 1 ,157     ,117,117.6,117.7
XS GIS Cut Line= 4
1633679.57617528516074.0180920461633523.53510808516231.477714402
1633437.00324354516438.586767232 1633272.4508454516620.161827247
#Sta/Elev= 30
       0  875.57      45  858.29    81.7  837.09     103  820.86   132.5  808.66
   152.4  793.02     174  782.66   209.7  761.63     219  758.64     249  753.61
   273.9  751.97  286.41 748.087   295.2  746.74  314.79748.0859   327.2  754.02
   412.6  755.26   433.9  756.65   453.9  761.17   472.5  771.75   484.1  785.39
     505  794.79   516.6  802.25   532.8   810.1   547.6  813.03   567.7  819.87
   581.4  831.02   607.2  844.46   630.1  859.83   662.9  873.44   691.2   890.4
#Mann= 6 ,-1,0
       0      .1       0  281.68     .07       0  286.41    .045       0
  314.79     .07       0  441.68     .06       0  506.14      .1       0
Bank Sta=286.41,314.79
XS Rating Curve= 0 ,0
Exp/Cntr(USF)=0,0
Exp/Cntr=0.3,0.1

Type RM Length L Ch R = 1 ,39      ,,,
XS GIS Cut Line= 4
1633585.43101884516019.039346285 1633418.8870786516183.932306789
1633356.65986363516321.4685944321633159.49954083516534.653970871
#Sta/Elev= 30
       0  870.55       8  866.46    24.2  861.94    40.5  855.21    67.3  834.95
      86   827.2   103.1  815.78   123.3  809.48   141.9  796.76   151.3  787.95
   170.9  772.89   198.2  758.15   216.5  752.46   285.4  750.72   293.1  747.25
   297.4  745.53   314.2  744.98     325  747.36   335.8  752.88   401.2  753.61
   421.4  762.79   437.6   764.1   449.3  767.62   475.8  780.69   511.9   807.3
   546.8  820.38   570.3  842.64   614.4  864.61   645.7  884.09   675.7  894.86
#Mann= 5 ,-1,0
       0      .1       0  254.36     .06       0   293.1    .045       0
     325     .06       0  525.32      .1       0
Bank Sta=293.1,325
XS Rating Curve= 0 ,0
Exp/Cntr(USF)=0,0
Exp/Cntr=0.3,0.1
LCMann Table=0

Chan Stop Cuts=-1
Use User Specified Reach Order=0
Composite Channel Slope=5